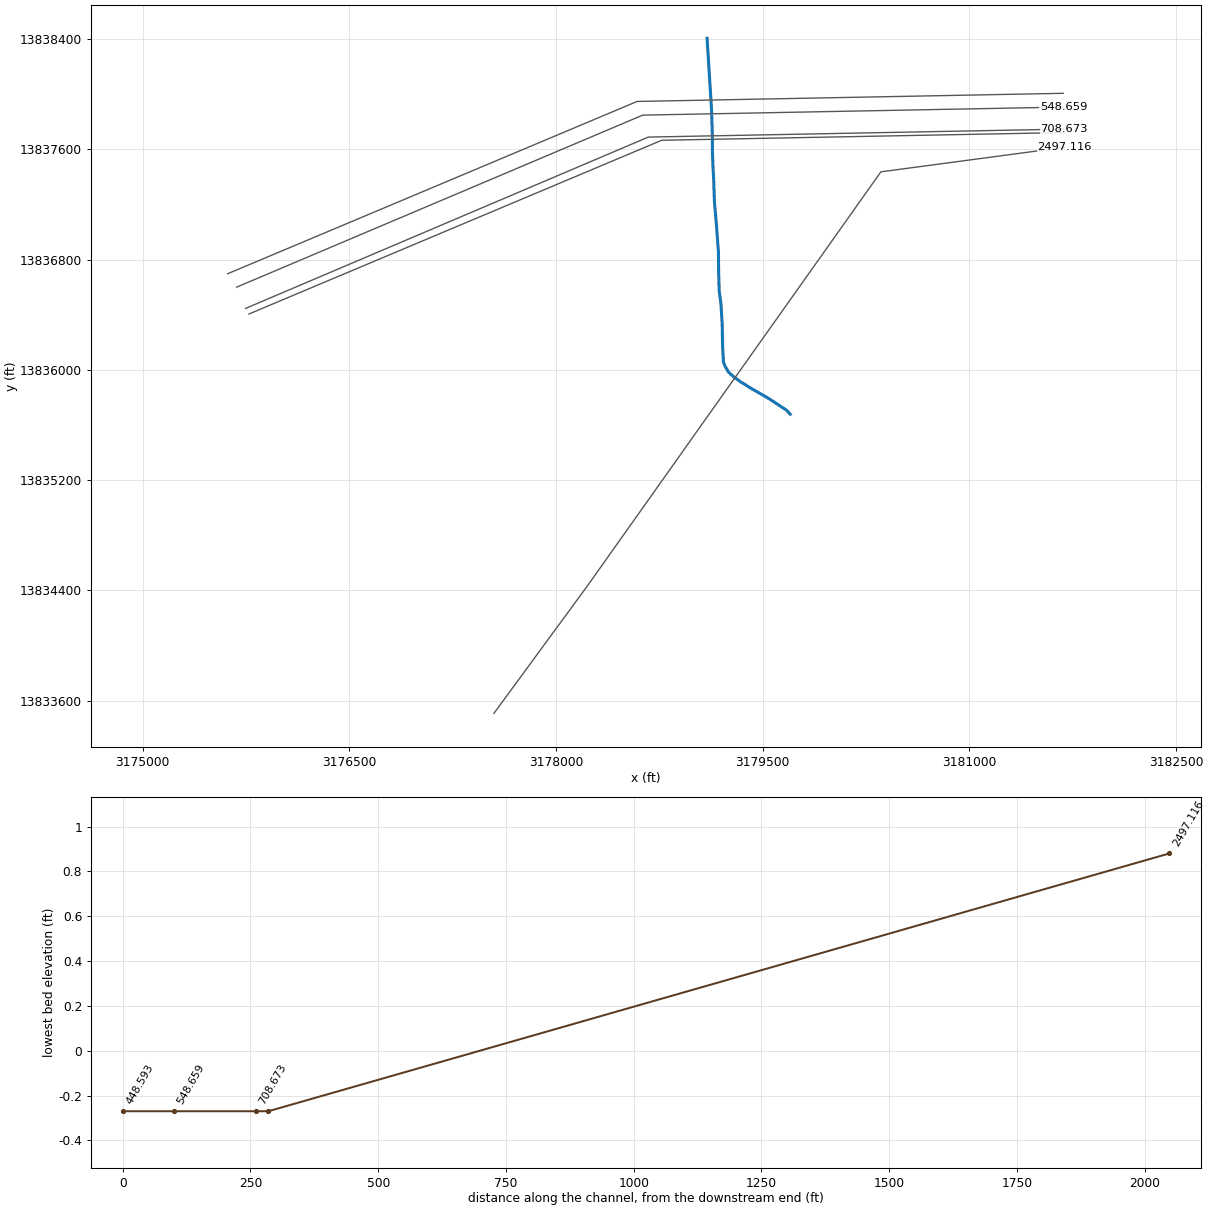
--- G109_00_00.prj (project) ---

Proj Title=G109-00-00
Current Plan=p01
Default Exp/Contr=.3,.1
English Units
Geom File=g01
Geom File=g02
Flow File=f03
Flow File=f04
Plan File=p01
Plan File=p02
Y Axis Title=Elevation
X Axis Title(PF)=Main Channel Distance
X Axis Title(XS)=Station
BEGIN DESCRIPTION:
San Jacinto
Buffalo Bayou Trib 6.77
G109-00-00
Flood Hazard Model
10, 2, 1, 0.2% Event
Filename G109_00_00.prj
Prepared by: Matthew Fischer Date: 2-25-04
Reviewd by:                              Date:
STATUS Final Submittal
END DESCRIPTION:
DSS Export Rating Curves= 0
DSS Export Rating Curve Sorted= 0
DSS Export Volume Flow Curves= 0
DXF OffsetX= 0
DXF OffsetY= 0
DXF ScaleX= 1
DXF ScaleY= 10

--- G109_00_00.p01 (plan) ---

Plan Title=FEMA Effective June 2007
Version=Version 3.0.1  Mar 2001
Short Identifier=FEMAeff0607
Geom File=g01
Flow File=f03
Subcritical Flow
K Sum by GR= 0
Std Step Tol= 0.003
Critical Tol= 0.003
Num of Std Step Trials= 20
Max Error Tol= 0.1
Flow Tol Ratio= 0.001
Split Flow NTrial= 30
Split Flow Tol= 0.02
Split Flow Ratio= 0.02
Log Output Level= 0
Friction Slope Method= 0
Unsteady Friction Slope Method= 2
Secant Critical Depth
Global Vel Dist= 0 , 0 , 0
Global Log Level= 0
CheckData=True
Encroach Param=-1 ,0,0, 0
Computation Interval=1HOUR
Output Interval=1HOUR
Run HTab= 0
Run UNet= 0
Run PostProcess= 0
UNET Theta= 1
UNET ZTol= 0.02
UNET ZSATol= 0.1
UNET MxIter= 20
UNET MaxInSteps= 20
UNET DtIC= 0
UNET DtMin= 0
UNET MaxCRTS= 20
UNET WFStab= 2
UNET SFStab= 1
UNET WFX= 1
UNET SFX= 1
UNET Convert EG Bridges=-1
UNET Use Existing IB Tables=-1
Instantaneous Interval=1HOUR
Write IC File= 0
IC Time=0
Write Velocity= 0
Write Detailed= 0

--- G109_00_00.p02 (plan) ---

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Plan Title=Floodway
Short Identifier=Floodway0607
Geom File=g01
Flow File=f04
Encroach Param=-1 ,0,0, 2
Encroach River=G109-00-00
Encroach Reach=G109-00-00_0004
Encroach Node=2497.116
       1    4950    5045
Encroach Node=733.676
       1    4850 5034.51
Encroach Node=708.673
       1    4850    5030
Encroach Node=628
       1    4850    5030
Encroach Node=548.659
       1    4850    5030
Encroach Node=448.593
       1    4970    5030

--- G109_00_00.f03 (steady flow) ---

Flow Title=FEMA Effective June 2007
Version=Version 3.0.1  Mar 2001
Number of Profiles= 4
Profile Names=10PCT_10yr, 2PCT_50yr, 1PCT_100yr, 0.2PCT_500yr
River Rch & RM=G109-00-00,G109-00-00_0004      ,2497.116
     710    1001    1154    1580
River Rch & RM=G109-00-00,G109-00-00_0004      ,733.676
     713    1005    1159    1588
Boundary for River Rch & Prof#=G109-00-00,G109-00-00_0004      , 1
Up Type= 0
Dn Type= 3
Dn Slope=.0004
DSS Import GetInterval= 0
DSS Import GetPeak= 0
DSS Import FillOption= 0

--- G109_00_00.f04 (steady flow) ---

Flow Title=Floodway
Version=Version 3.0.1  Mar 2001
Number of Profiles= 2
Profile Names=1PCT_100yr, 1PCTFloodway_100yrFW
River Rch & RM=G109-00-00,G109-00-00_0004      ,2497.116
    1154    1154
River Rch & RM=G109-00-00,G109-00-00_0004      ,733.676
    1159    1159
Boundary for River Rch & Prof#=G109-00-00,G109-00-00_0004      , 1
Up Type= 0
Dn Type= 3
Dn Slope=.0004
DSS Import GetInterval= 0
DSS Import GetPeak= 0
DSS Import FillOption= 0

--- G109_00_00.g01 (geometry) ---

Geom Title=G109-00-00 June 2007
Version=Version 3.0.1  Mar 2001

River Reach=G109-00-00   ,G109-00-00_0004
Reach XY= 30
     3179699.745    13835679.008     3179670.728    13835709.357
     3179540.097    13835795.328     3179417.282    13835865.668
       3179347.5    13835909.326     3179333.719    13835917.949
     3179289.841    13835950.211     3179252.039    13835984.017
     3179227.897    13836025.061     3179214.992    13836056.033
     3179208.539    13836181.213     3179205.958    13836332.202
     3179196.925    13836481.902     3179184.019    13836576.109
     3179183.556      13836592.5     3179183.526    13836593.526
     3179180.148    13836712.903     3179178.857    13836853.569
     3179164.662    13837047.145     3179149.176    13837225.236
     3179144.014    13837393.002     3179140.142    13837449.784
      3179134.98     13837591.74      3179134.98     13837691.11
     3179128.527    13837892.429     3179128.374    13837894.879
     3179126.984    13837916.984     3179119.726      13838032.5
     3179116.092    13838090.315     3179096.234    13838406.333

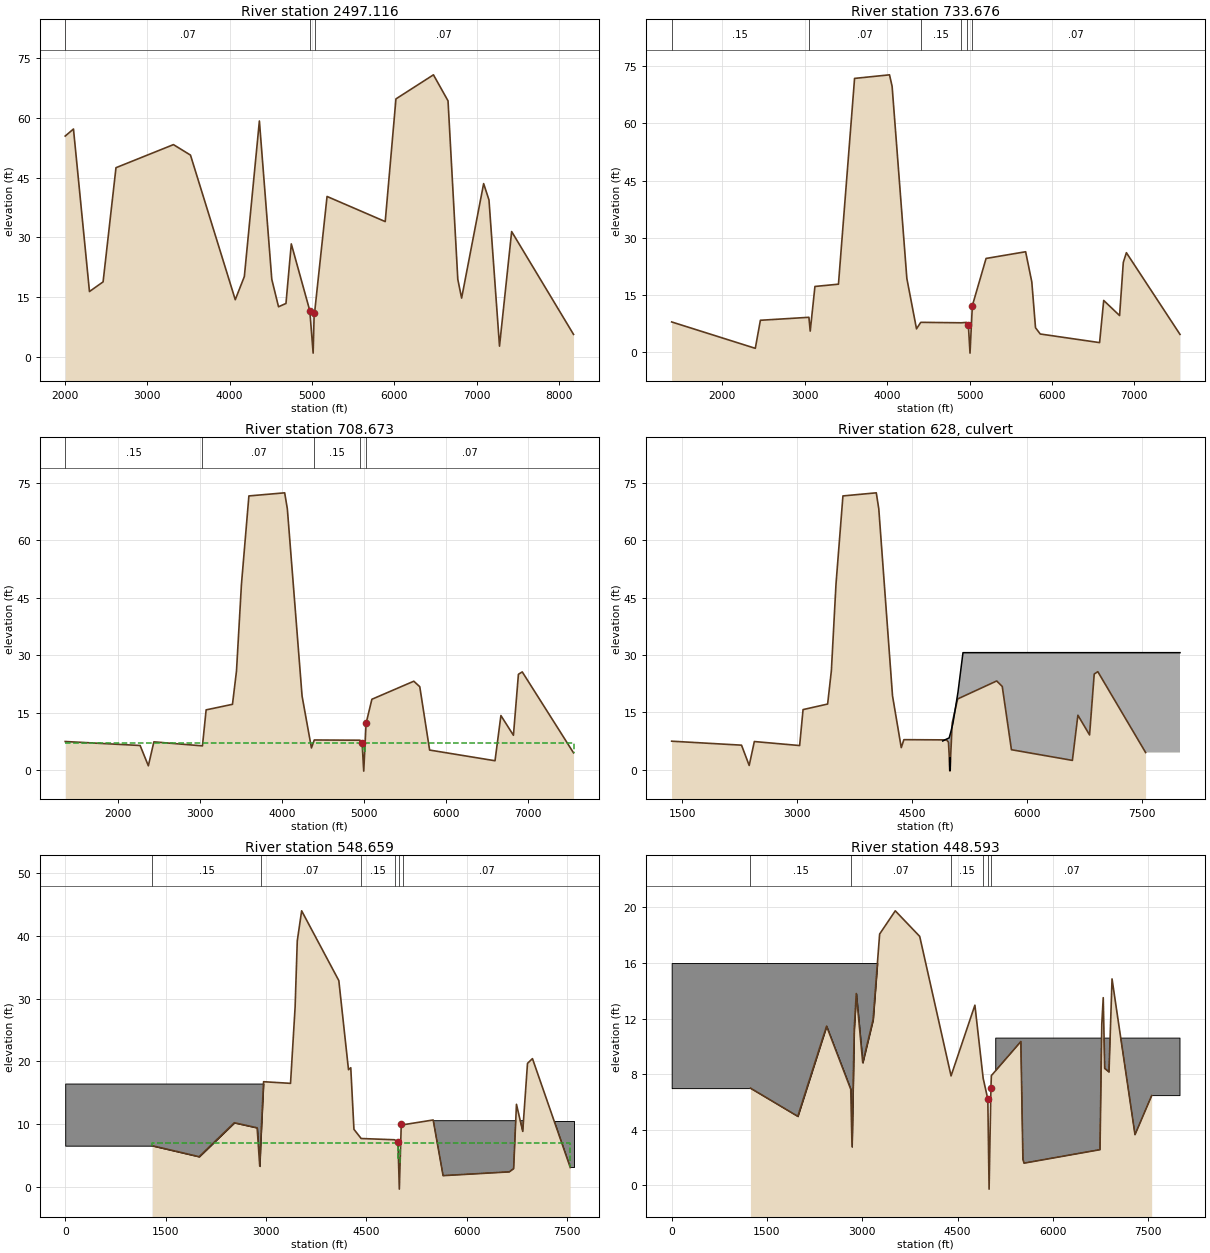
Type RM Length L Ch R = 1 ,2497.116,1857.57,1763.44,1669.3
XS GIS Cut Line= 4
     3177549.788    13833508.323     3178236.006    13834444.445
     3180357.442    13837437.646     3181689.533      13837615.6
#Sta/Elev= 30
 2002.83   55.43 2103.19    57.2 2297.51   16.36    2463   18.79 2619.47   47.48
 3317.42   53.28 3524.22   50.65 4068.16   14.31 4178.47   20.13  4361.1   59.22
 4511.74   19.42 4593.57   12.53 4683.89   13.36 4748.65   28.33 4973.37   11.55
 5013.87     .88 5026.63   10.93 5033.85   11.49 5182.83   40.25 5889.23   33.94
 6019.58   64.77 6474.95   70.82 6652.04   64.28 6770.82   19.41 6817.06   14.71
 7084.56   43.48 7149.42   39.37  7277.2    2.63 7424.69   31.43 8176.21    5.59
#Mann= 3 ,-1 , 0
 2002.83     .07       0 4973.37    .035       0 5033.85     .07       0
#Block Obstruct= 2 , 0
         4786.77   23.97 5381.92           34.48
Bank Sta=4973.37,5026.63
XS Rating Curve= 0
Exp/Cntr=.3,.1

Type RM Length L Ch R = 1 ,733.676 ,25,25,25
XS GIS Cut Line= 3
     3175772.132    13836406.145     3178767.313    13837666.741
     3181685.401    13837722.552
#Sta/Elev= 30
  1385.4    7.91 2400.24     .99 2461.94    8.35 3050.83    9.13  3066.6    5.51
 3123.87   17.22 3409.25   17.82 3604.77   71.81 4028.72   72.75 4060.22   69.75
 4239.24   19.32 4356.37     6.1 4407.85    7.81 4901.31    7.69 4962.99    7.79
 4985.49    7.19 5005.61    -.27 5028.16    9.63 5034.51   12.22  5200.5   24.57
 5680.42   26.33 5755.44   18.41 5800.45    6.39 5857.83    4.75 6577.88    2.49
 6627.95   13.55 6820.63    9.59 6865.64   23.53 6903.26   26.08 7553.67    4.65
#Mann= 6 ,-1 , 0
  1385.4     .15       0 3050.83     .07       0 4407.85     .15       0
 4901.31     .07       0 4962.99    .035       0 5028.16     .07       0
#Block Obstruct= 2 , 0
         3739.54   26.66 5213.23           21.62
Bank Sta=4985.49,5034.51
XS Rating Curve= 0
Exp/Cntr=.5,.3

Type RM Length L Ch R = 1 ,708.673 ,160.01,160.01,160.01
XS GIS Cut Line= 3
     3175747.781     13836446.73     3178670.086    13837689.886
     3181684.923    13837747.547
#Sta/Elev= 30
 1359.62    7.46 2272.16    6.42 2372.33    1.12 2439.54    7.37 3031.22    6.32
 3075.94   15.72 3396.92   17.17 3445.82   25.88 3506.14   48.49 3596.88   71.57
 4032.65   72.38 4065.26   68.18 4244.57   19.32 4358.67    5.78 4393.27    7.86
 4950.47     7.8 4975.49    7.19 4995.61    -.27 5018.16    9.63 5024.51   12.22
 5094.79   18.49 5605.35    23.2 5677.98   21.77    5798    5.23 6594.47    2.44
  6666.3   14.24 6818.71    9.09 6879.53   25.01 6926.32   25.63 7550.74     4.5
#Mann= 5 ,-1 , 0
 1359.62     .15       0 3031.22     .07       0 4393.27     .15       0
 4950.47    .035       0 5018.16     .07       0
#XS Ineff= 2 , 0
       0    4983       7    5007       0       7
Permanent Ineff=
       F       F
#Block Obstruct= 2 , 0
         3626.18   23.75 5194.33           18.32
Bank Sta=4975.49,5024.51
XS Rating Curve= 0
Exp/Cntr=.5,.3

Type RM Length L Ch R = 2 ,628     ,,,
BEGIN DESCRIPTION:
Plant/Pipeline Crossing (see below)
Large Resevoir Blocking Flow on Right
END DESCRIPTION:
Bridge Culvert--1,0,-1,-1, 0
Deck Dist Width WeirC Skew NumUp NumDn MinLoCord MaxHiCord MaxSubmerge Is_Ogee
33,93,2.6,0, 8, 8, , , .95, 0, 0,0,,
    4900    4963    4984    5005    5034    5100    5165    8000
    7.51    8.13     8.3    9.81   12.12   20.32    30.6    30.6
                                                                
    4900    4963    4984    5005    5034    5100    5165    8000
    7.51    8.13     8.3    9.81   12.12   20.32    30.6    30.6
                                                                
Culvert=1,3.5,,93,.012,.2,1,1,1,-.344,4991,-.8541,4991,Culvert #3  , 0 ,33
Culvert Bottom n=.012
Culvert=1,3.5,,93,.012,.2,1,1,1,-.364,4995,-.803,4995,Culvert #1  , 0 ,33
Culvert Bottom n=.012
Culvert=1,3.5,,93,.012,.2,1,1,1,-.264,4999,-.8541,4999,Culvert #2  , 0 ,33
Culvert Bottom n=.012
BC Design=,, 0 ,, 0 ,,,,,,

Type RM Length L Ch R = 1 ,548.659 ,100.07,100.07,100.06
XS GIS Cut Line= 3
     3175682.844    13836600.956     3178629.249    13837849.135
     3181681.864    13837907.518
#Sta/Elev= 30
 1298.19    6.63 2002.82    4.88 2528.58   10.27 2869.54    9.47 2908.74    3.37
 2923.98    7.51 2965.96   16.79  3368.8   16.53 3437.29   28.63 3469.62   39.15
 3535.04   43.93 4090.96   32.85 4235.53    18.7 4269.48   19.01 4316.98    9.23
 4424.72    7.77 4924.96    7.57 4975.49    7.19 4995.61    -.27 5024.51    10.1
 5050.02    9.95 5501.51   10.71 5649.85    1.87 6640.16    2.47 6704.67    2.98
 6746.73    13.2 6840.56     8.9 6911.76    19.7 6985.99   20.46 7551.24    3.17
#Mann= 6 ,-1 , 0
 1298.19     .15       0 2923.98     .07       0 4424.72     .15       0
 4924.96     .07       0 4995.61    .035       0 5050.02     .07       0
#XS Ineff= 2 , 0
       0    4983       7    5007       0       7
Permanent Ineff=
       F       F
#Block Obstruct= 3 ,-1
       0    3323    16.5    5500    7600    10.6    5250    5310     9.8
Bank Sta=4975.49,5024.51
XS Rating Curve= 0
Exp/Cntr=.5,.3

Type RM Length L Ch R = 1 ,448.593 ,444.23,448.59,452.96
XS GIS Cut Line= 3
     3175617.906    13836698.362     3178588.783    13837948.379
     3181679.951      13838007.5
#Sta/Elev= 30
 1239.49       7  1984.9    4.97 2437.88   11.46 2818.21    6.92  2838.3    2.78
 2872.66   11.22 2905.51   13.81 3007.01    8.83 3170.09   11.93 3272.99   18.09
 3519.22   19.76 3903.54   17.92 4396.93    7.88 4772.21   12.97 4902.12    7.71
 4975.49    6.21 4995.61    -.27 5024.51       7 5031.32     7.9 5495.41   10.35
  5527.8    1.88 5545.61     1.6 6741.22    2.57 6769.26   11.61 6791.99   13.51
 6814.71    8.42 6882.87    8.16 6930.42   14.86 7291.86    3.65 7554.37    6.46
#Mann= 6 ,-1 , 0
 1239.49     .15       0 2818.21     .07       0 4396.93     .15       0
 4902.12     .07       0 4975.49    .035       0 5031.32     .07       0
#Block Obstruct= 2 ,-1
       0    3371      16    5100    8000    10.6
Bank Sta=4975.49,5024.51
XS Rating Curve= 0
Exp/Cntr=.3,.1

Chan Stop Cuts=-1

--- G109_00_00.g02 (geometry) ---

Geom Title=G109-00-00 June 2007 (Floodway)
Version=Version 3.0.1  Mar 2001

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
River Reach=G109-00-00   ,G109-00-00_0004